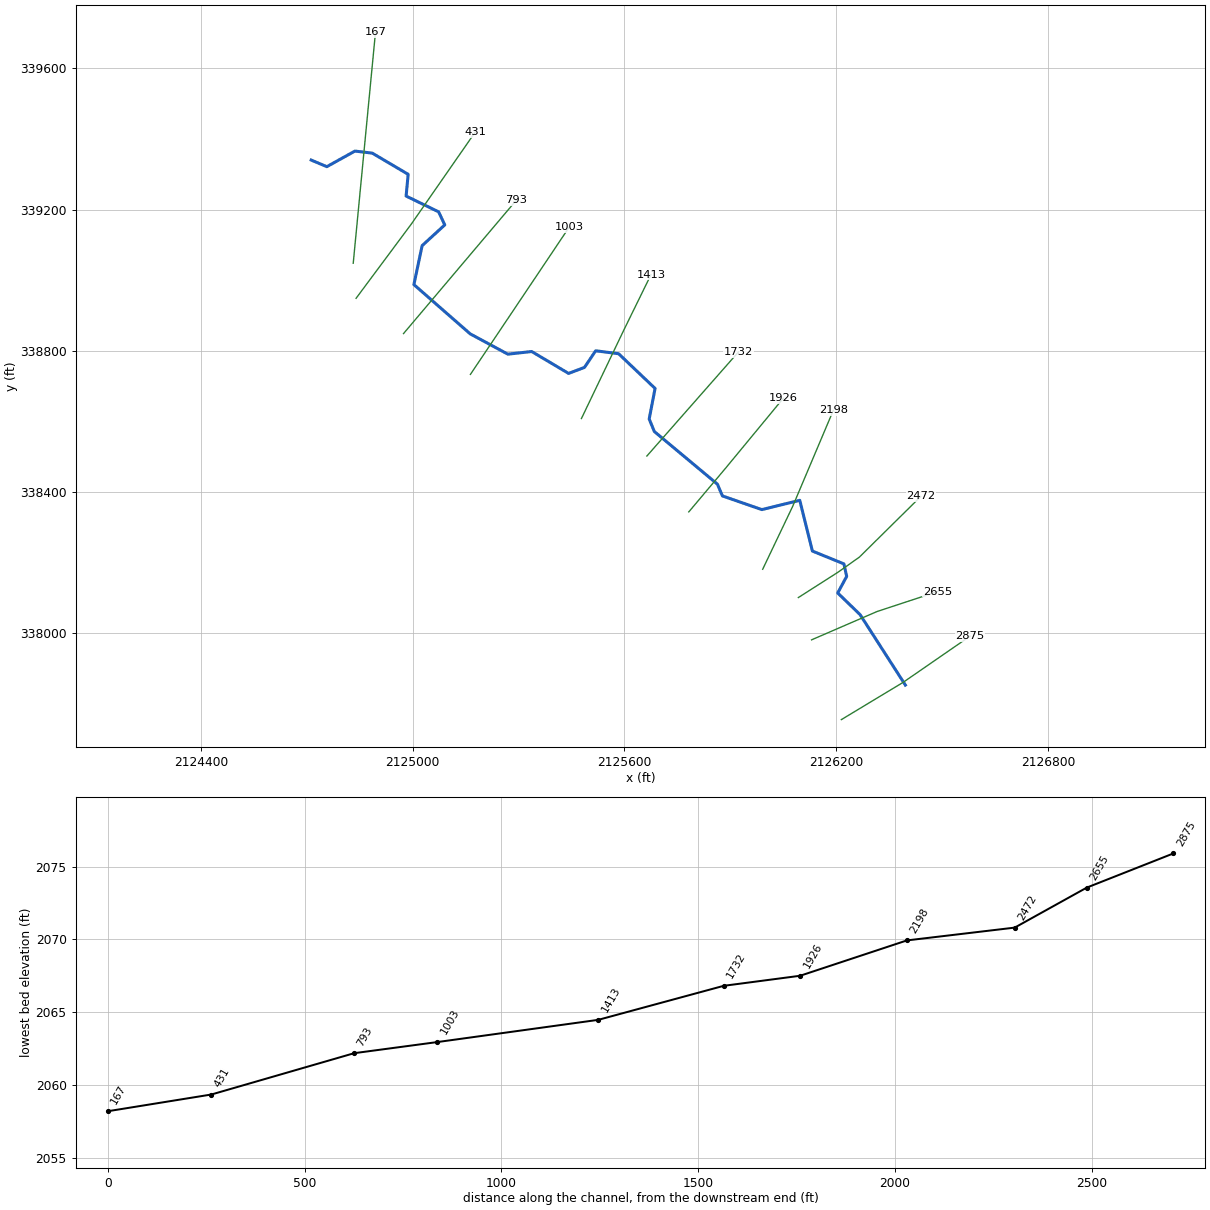
--- BURNSRNT1.prj (project) ---

Proj Title=BURNSRNT1
Current Plan=p01
Default Exp/Contr=0.3,0.1
English Units
Geom File=g01
Flow File=f01
Plan File=p01
Y Axis Title=Elevation
X Axis Title(PF)=Main Channel Distance
X Axis Title(XS)=Station
BEGIN DESCRIPTION:
Stream Name- Burns Run Tributary 1
Flood Zone: Zone A
Greenbrier County, WV
County-Wide Study
WVDHSEM-2018-3, Flood Risk Project
HEC-RAS Version: 5.0.7
General Notes:
For the Hydrology regression was used.
END DESCRIPTION:
DSS Export Rating Curves= 0
DSS Export Rating Curve Sorted= 0
DSS Export Volume Flow Curves= 0
DXF Filename=BURNSRNT1.G2.
DXF OffsetX= 0
DXF OffsetY= 0
DXF ScaleX= 1
DXF ScaleY= 10

--- BURNSRNT1.p01 (plan) ---

Plan Title=Floodplain
Program Version=5.07
Short Identifier=Floodplain
Geom File=g01
Flow File=f01
Subcritical Flow
K Sum by GR= 0
Std Step Tol= 0.01
Critical Tol= 0.01
Num of Std Step Trials= 20
Max Error Tol= 0.3
Flow Tol Ratio= 0.001
Split Flow NTrial= 30
Split Flow Tol= 0.02
Split Flow Ratio= 0.02
Log Output Level= 0
Friction Slope Method= 1
Unsteady Friction Slope Method= 2
Unsteady Bridges Friction Slope Method= 1
Parabolic Critical Depth
Global Vel Dist= 0 , 0 , 0
Global Log Level= 0
CheckData=True
Encroach Param=-1 ,0,0, 0
Computation Interval=1MIN
Output Interval=1HOUR
Instantaneous Interval=1HOUR
Mapping Interval=1HOUR
Computation Time Step Use Courant=        0
Computation Time Step Use Time Series=    0
Computation Time Step Count To Double=0
Computation Time Step Max Doubling=0
Computation Time Step Max Halving=0
Computation Time Step Residence Courant=0
Run HTab= 0
Run UNet= 0
Run Sediment= 0
Run PostProcess= 0
Run WQNet= 0
Run RASMapper= 0
UNET Theta= 1
UNET Theta Warmup= 1
UNET ZTol= 0.02
UNET ZSATol= 0.02
UNET MxIter= 20
UNET Max Iter WO Improvement= 0
UNET MaxInSteps= 0
UNET DtIC= 0
UNET DtMin= 0
UNET MaxCRTS= 20
UNET WFStab= 2
UNET SFStab= 1
UNET WFX= 1
UNET SFX= 1
UNET 1D Methodology=Finite Difference
UNET DSS MLevel= 4
UNET Pardiso=0
UNET DZMax Abort= 100
UNET Use Existing IB Tables=-1
UNET Froude Reduction=False
UNET Froude Limit= 0.8
UNET Froude Power= 4
UNET D1 Cores= 0
UNET D2 Coriolis=0
UNET D2 Cores= 0
UNET D2 Theta= 1
UNET D2 Theta Warmup= 1
UNET D2 Z Tol= 0.01
UNET D2 Volume Tol= 0.01
UNET D2 Max Iterations= 20
UNET D2 Equation= 0
UNET D2 RampUpFraction=0.1
UNET D2 TimeSlices= 1
UNET D2 BCVolumeCheck=0
UNET D1D2 MaxIter= 0
UNET D1D2 ZTol=0.01
UNET D1D2 QTol=0.1
UNET D1D2 MinQTol=1
Write IC File= 0
Write IC File at Fixed DateTime=0
Write IC File at Sim End=0
Echo Input=False
Echo Parameters=False
Echo Output=False
Write Detailed= 0
HDF Write Warmup=0
HDF Write Time Slices=0
HDF Flush=0
HDF Face Node Velocities=0
HDF Compression= 1
HDF Chunk Size= 1
HDF Spatial Parts= 1
HDF Use Max Rows=0
HDF Fixed Rows= 1
Calibration Method= 0
Calibration Iterations= 20
Calibration Max Change=0.05
Calibration Tolerance=0.2
Calibration Maximum=1.5
Calibration Minimum=0.5
Calibration Optimization Method= 1
WQ AD Non Conservative
WQ ULTIMATE=-1
WQ Max Comp Step=1HOUR
WQ Output Interval=15MIN
WQ Output Selected Increments= 0
WQ Output face flow=0
WQ Output face velocity=0
WQ Output face area=0
WQ Output face dispersion=0
WQ Output cell volume=0
WQ Output cell surface area=0
WQ Output cell continuity=0
WQ Output cumulative cell continuity=0
WQ Output face conc=0
WQ Output face dconc_dx=0
WQ Output face courant=0
WQ Output face peclet=0
WQ Output face adv mass=0
WQ Output face disp mass=0
WQ Output cell mass=0
WQ Output cell source sink temp=0
WQ Output nsm pathways=0
WQ Output nsm derived pathways=0
WQ Output MaxMinRange=-1
WQ Daily Max Min Mean=-1
WQ Daily Range=0
WQ Daily Time=0
WQ Create Restart=0
WQ Fixed Restart=0
WQ System Summary=0
WQ Write To DSS=0
WQ Use Fixed Temperature=0
Sorting and Armoring Iterations= 10
XS Update Threshold= 0.02
Bed Roughness Predictor= 0
Hydraulics Update Threshold= 0.02
Energy Slope Method= 1
Volume Change Method= 1
Sediment Retention Method= 0
XS Weighting Method= 0
Number of US Weighted Cross Sections= 1
Number of DS Weighted Cross Sections= 1
Upstream XS Weight=0
Main XS Weight=1
Downstream XS Weight=0
Number of DS XS's Weighted with US Boundary= 1
Upstream Boundary Weight= 1
Weight of XSs Associated with US Boundary= 0
Number of US XS's Weighted with DS Boundary= 1
Downstream Boundary Weight= 0.5
Weight of XSs Associated with DS Boundary= 0.5
Percentile Method= 0
Sediment Output Level= 3
Mass or Volume Output= 0
Output Increment Type= 1
Profile and TS Output Increment= 1
XS Output Flag= 0
XS Output Increment= 10
Write Gradation File= 0
Read Gradation Hotstart= 0
Write HDF5 File= 1
Write Binary Output= 1
Write DSS Sediment File= 0
SV Curve= 0
Specific Gage Flag= 0

--- BURNSRNT1.f01 (steady flow) ---

Flow Title=Flow
Program Version=5.07
Number of Profiles= 6
Profile Names=f1p,f10p,f4p,f2p,f02p,f1pplus
River Rch & RM=BURNSRN,Main            ,9203
     572     302     402     484     799     846
River Rch & RM=BURNSRN,Main            ,7195
     649     345     457     550     905     960
River Rch & RM=BURNSRN,Main            ,4526
    1220     661     867    1040    1670    1800
River Rch & RM=BURNSRNT1,Main            ,2875
     504     265     353     426     705     745
River Rch & RM=BURNSRNT1,Main            ,2198
     669     356     472     568     932     990
River Rch & RM=CLBRSNCKT1,Main            ,2948
     116    57.4    78.7    96.5     166     171
River Rch & RM=CLBRSNCKT1,Main            ,2280
     138    69.1    94.4     116     198     210
River Rch & RM=CLBRSNCKT1,Main            ,1216
     156    78.2     107     130     223     230
River Rch & RM=CLBRSNCKT1,Main            ,243
     178    89.6     122     149     253     300
River Rch & RM=CLBRSNCKT2,Main            ,5369
     223     114     154     187     317     330
River Rch & RM=CLBRSNCKT2,Main            ,3799
     483     253     338     408     676     714
River Rch & RM=INDIANCK,Main            ,11519
     313     162     218     264     443     463
River Rch & RM=INDIANCK,Main            ,9807
     520     274     365     440     728     769
River Rch & RM=INDIANCK,Main            ,8108
     581     307     409     492     812     860
River Rch & RM=INDIANCK,Main            ,6227
     647     344     456     549     902     958
River Rch & RM=LTROARCK,Main            ,4000
     648     344     456     549     903     958
River Rch & RM=MLGNCKTR5,Main            ,7678
     581     307     409     492     812     860
River Rch & RM=MLGNCKTR5,Main            ,5118
     654     347     461     554     911     967
River Rch & RM=MLGNCKTR5,Main            ,2636
     728     388     514     617    1010    1080
River Rch & RM=ROARINGCK,Main            ,17918
     544     287     382     461     761     805
River Rch & RM=ROARINGCK,Main            ,16996
     613     325     431     519     855     906
River Rch & RM=ROARINGCK,Main            ,14906
     713     380     504     605     992    1060
River Rch & RM=ROARINGCK,Main            ,11661
     864     464     612     734    1200    1280
River Rch & RM=ROARINGCK,Main            ,8657
     964     520     685     820    1330    1430
River Rch & RM=ROARINGCK,Main            ,4987
    1570     861    1120    1340    2150    2320
Boundary for River Rch & Prof#=BURNSRN,Main            , 1
Up Type= 0
Dn Type= 3
Dn Slope=0.0012
Boundary for River Rch & Prof#=BURNSRN,Main            , 2
Up Type= 0
Dn Type= 3
Dn Slope=0.0012
Boundary for River Rch & Prof#=BURNSRN,Main            , 3
Up Type= 0
Dn Type= 3
Dn Slope=0.0012
Boundary for River Rch & Prof#=BURNSRN,Main            , 4
Up Type= 0
Dn Type= 3
Dn Slope=0.0012
Boundary for River Rch & Prof#=BURNSRN,Main            , 5
Up Type= 0
Dn Type= 3
Dn Slope=0.0012
Boundary for River Rch & Prof#=BURNSRN,Main            , 6
Up Type= 0
Dn Type= 3
Dn Slope=0.0012
Boundary for River Rch & Prof#=BURNSRNT1,Main            , 1
Up Type= 0
Dn Type= 3
Dn Slope=0.00496
Boundary for River Rch & Prof#=BURNSRNT1,Main            , 2
Up Type= 0
Dn Type= 3
Dn Slope=0.00496
Boundary for River Rch & Prof#=BURNSRNT1,Main            , 3
Up Type= 0
Dn Type= 3
Dn Slope=0.00496
Boundary for River Rch & Prof#=BURNSRNT1,Main            , 4
Up Type= 0
Dn Type= 3
Dn Slope=0.00496
Boundary for River Rch & Prof#=BURNSRNT1,Main            , 5
Up Type= 0
Dn Type= 3
Dn Slope=0.00496
Boundary for River Rch & Prof#=BURNSRNT1,Main            , 6
Up Type= 0
Dn Type= 3
Dn Slope=0.00496
Boundary for River Rch & Prof#=CLBRSNCKT1,Main            , 1
Up Type= 0
Dn Type= 3
Dn Slope=0.00848
Boundary for River Rch & Prof#=CLBRSNCKT1,Main            , 2
Up Type= 0
Dn Type= 3
Dn Slope=0.00848
Boundary for River Rch & Prof#=CLBRSNCKT1,Main            , 3
Up Type= 0
Dn Type= 3
Dn Slope=0.00848
Boundary for River Rch & Prof#=CLBRSNCKT1,Main            , 4
Up Type= 0
Dn Type= 3
Dn Slope=0.00848
Boundary for River Rch & Prof#=CLBRSNCKT1,Main            , 5
Up Type= 0
Dn Type= 3
Dn Slope=0.00848
Boundary for River Rch & Prof#=CLBRSNCKT1,Main            , 6
Up Type= 0
Dn Type= 3
Dn Slope=0.00848
Boundary for River Rch & Prof#=CLBRSNCKT2,Main            , 1
Up Type= 0
Dn Type= 3
Dn Slope=0.00274
Boundary for River Rch & Prof#=CLBRSNCKT2,Main            , 2
Up Type= 0
Dn Type= 3
Dn Slope=0.00274
Boundary for River Rch & Prof#=CLBRSNCKT2,Main            , 3
Up Type= 0
Dn Type= 3
Dn Slope=0.00274
Boundary for River Rch & Prof#=CLBRSNCKT2,Main            , 4
Up Type= 0
Dn Type= 3
Dn Slope=0.00274
Boundary for River Rch & Prof#=CLBRSNCKT2,Main            , 5
Up Type= 0
Dn Type= 3
Dn Slope=0.00274
Boundary for River Rch & Prof#=CLBRSNCKT2,Main            , 6
Up Type= 0
Dn Type= 3
Dn Slope=0.00274
Boundary for River Rch & Prof#=INDIANCK,Main            , 1
Up Type= 0
Dn Type= 3
Dn Slope=0.00176
Boundary for River Rch & Prof#=INDIANCK,Main            , 2
Up Type= 0
Dn Type= 3
Dn Slope=0.00176
Boundary for River Rch & Prof#=INDIANCK,Main            , 3
Up Type= 0
Dn Type= 3
Dn Slope=0.00176
Boundary for River Rch & Prof#=INDIANCK,Main            , 4
Up Type= 0
Dn Type= 3
Dn Slope=0.00176
Boundary for River Rch & Prof#=INDIANCK,Main            , 5
Up Type= 0
Dn Type= 3
Dn Slope=0.00176
Boundary for River Rch & Prof#=INDIANCK,Main            , 6
Up Type= 0
Dn Type= 3
Dn Slope=0.00176
Boundary for River Rch & Prof#=LTROARCK,Main            , 1
Up Type= 0
Dn Type= 3
Dn Slope=0.04436
Boundary for River Rch & Prof#=LTROARCK,Main            , 2
Up Type= 0
Dn Type= 3
Dn Slope=0.04436
Boundary for River Rch & Prof#=LTROARCK,Main            , 3
Up Type= 0
Dn Type= 3
Dn Slope=0.04436
Boundary for River Rch & Prof#=LTROARCK,Main            , 4
Up Type= 0
Dn Type= 3
Dn Slope=0.04436
Boundary for River Rch & Prof#=LTROARCK,Main            , 5
Up Type= 0
Dn Type= 3
Dn Slope=0.04436
Boundary for River Rch & Prof#=LTROARCK,Main            , 6
Up Type= 0
Dn Type= 3
Dn Slope=0.04436
Boundary for River Rch & Prof#=MLGNCKTR5,Main            , 1
Up Type= 0
Dn Type= 3
Dn Slope=0.0247
Boundary for River Rch & Prof#=MLGNCKTR5,Main            , 2
Up Type= 0
Dn Type= 3
Dn Slope=0.0247
Boundary for River Rch & Prof#=MLGNCKTR5,Main            , 3
Up Type= 0
Dn Type= 3
Dn Slope=0.0247
Boundary for River Rch & Prof#=MLGNCKTR5,Main            , 4
Up Type= 0
Dn Type= 3
Dn Slope=0.0247
Boundary for River Rch & Prof#=MLGNCKTR5,Main            , 5
Up Type= 0
Dn Type= 3
Dn Slope=0.0247
Boundary for River Rch & Prof#=MLGNCKTR5,Main            , 6
Up Type= 0
Dn Type= 3
Dn Slope=0.0247
Boundary for River Rch & Prof#=ROARINGCK,Main            , 1
Up Type= 0
Dn Type= 3
Dn Slope=0.01435
Boundary for River Rch & Prof#=ROARINGCK,Main            , 2
Up Type= 0
Dn Type= 3
Dn Slope=0.01435
Boundary for River Rch & Prof#=ROARINGCK,Main            , 3
Up Type= 0
Dn Type= 3
Dn Slope=0.01435
Boundary for River Rch & Prof#=ROARINGCK,Main            , 4
Up Type= 0
Dn Type= 3
Dn Slope=0.01435
Boundary for River Rch & Prof#=ROARINGCK,Main            , 5
Up Type= 0
Dn Type= 3
Dn Slope=0.01435
Boundary for River Rch & Prof#=ROARINGCK,Main            , 6
Up Type= 0
Dn Type= 3
Dn Slope=0.01435
DSS Import GetInterval= 0
DSS Import GetPeak= 0
DSS Import FillOption= 0

--- BURNSRNT1.g01 (geometry) ---

Geom Title=Geometry
Program Version=5.07

River Reach=BURNSRNT1       ,Main
Reach XY= 30
2126395.95949587337852.5087012052126267.60739037338052.209417284
2126204.27418372338113.4592947812126229.69079953338160.542533949
 2126221.7741487338195.9594578592126132.60733229338232.209385365
2126096.77407062338375.9594259562125989.27395755338349.709478453
 2125877.6075142338388.4594009522125863.44054779338421.792667612
2125684.69057721338570.9593640272125670.10727304338606.375959858
2125686.77390638338693.0427812782125583.44077972338791.375917941
2125518.44058162 338799.709234612125486.77397829338752.625995442
 2125441.7740683338735.5426962822125337.19061604338797.625905454
2125269.69075105338790.1259204452125163.02396962338847.626133531
2125003.44062737338987.2091877012125026.77391404339097.625961617
2125090.94078046339156.3758441212125073.44081545339193.459431365
2124981.35733822339238.0426755252124987.19065988 339299.70921886
2124885.52386847339359.7094269542124836.35730013339365.542748615
2124756.77412596339321.3758421992124712.36378172339340.118586868

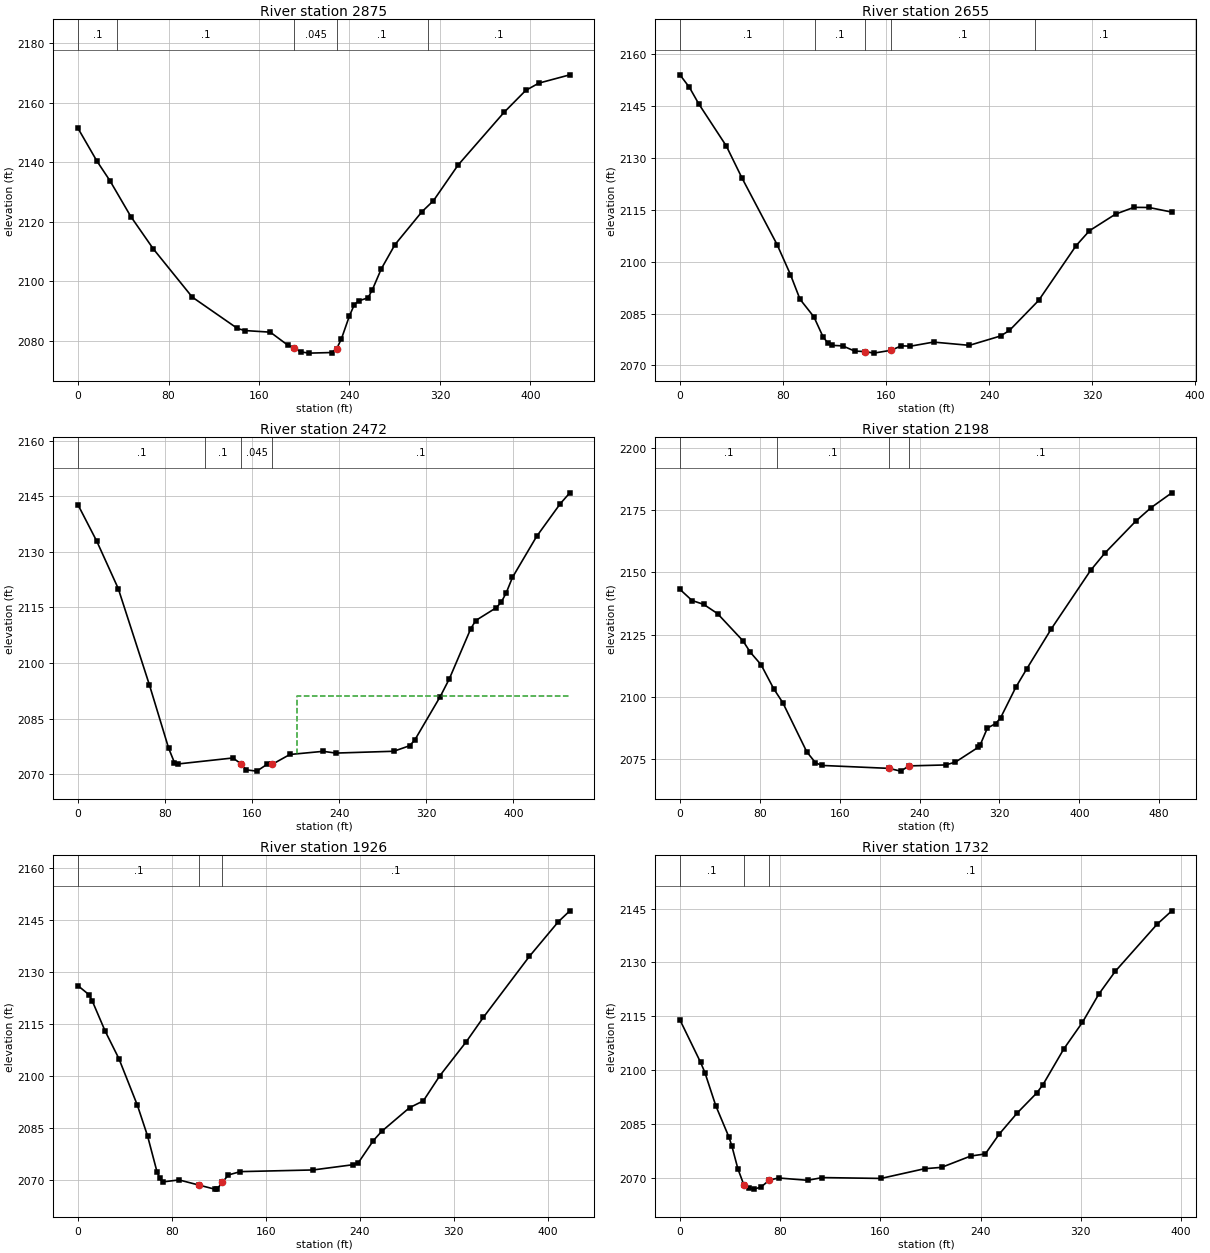
Type RM Length L Ch R = 1 ,2875    ,220.5,220.2,218
XS GIS Cut Line= 3
2126214.62226012337754.6489887832126389.52709404337860.164853871
2126579.20552045337991.107505366
#Sta/Elev= 30
       0 2151.43    16.7 2140.43    28.2 2133.85    46.7 2121.79    66.5 2110.96
     101 2094.73   140.9 2084.21   147.3  2083.5     170 2082.95   185.3 2078.63
   191.32077.595   196.8 2076.33   204.3 2075.91   224.4 2076.11  228.642077.411
   232.8 2080.63   239.8 2088.27   244.3 2092.23   248.3 2093.49   256.4 2094.49
   260.3 2097.27   268.1 2104.21   280.2 2112.36   304.1 2123.43   314.2  2127.1
     336 2139.09   376.6 2156.78   395.8 2164.16   407.3  2166.6   434.8  2169.4
#Mann= 5 ,-1 , 0
       0      .1       0   34.65      .1       0   191.3    .045       0
  228.64      .1       0  309.05      .1       0
Bank Sta=191.3,228.64
XS Rating Curve= 0 ,0
Exp/Cntr=0.3,0.1

Type RM Length L Ch R = 1 ,2655    ,177.4,183.1,183.3
XS GIS Cut Line= 3
 2126130.2471008337980.6908595262126315.66405278338060.899032444
2126486.49737254338117.148919955
#Sta/Elev= 30
       0 2153.99     7.4 2150.33    14.6 2145.59      36 2133.42    48.3 2124.07
    75.4 2104.95    85.8 2096.26    93.2 2089.14     104 2084.05   111.1 2078.27
   114.7 2076.55   118.2 2075.81   126.4 2075.65   135.7 2074.14  143.892074.019
   150.4 2073.56  163.92 2074.38   171.9 2075.67     179 2075.57   196.9 2076.75
   224.7 2075.81   248.9 2078.51   255.8  2080.1   278.5 2088.78   307.6 2104.62
     318 2108.94   338.2 2113.73   352.5 2115.69   364.2 2115.65   381.9 2114.32
#Mann= 5 ,-1 , 0
       0      .1       0  104.82      .1       0  143.89    .045       0
  163.92      .1       0  275.46      .1       0
Bank Sta=143.89,163.92
XS Rating Curve= 0 ,0
Exp/Cntr=0.3,0.1

Type RM Length L Ch R = 1 ,2472    ,263.8,273.9,273.5
XS GIS Cut Line= 4
2126092.74717578338100.4822866172126205.24727887338172.357470945
2126265.66382471338215.065718859 2126439.6221382338386.940703198
#Sta/Elev= 30
       0 2142.65    17.3  2132.8      37 2120.05    65.7    2094    83.3 2076.98
    88.6 2073.13    91.5 2072.73   142.4 2074.36  149.582072.827   154.5 2071.15
   164.3 2070.81   173.7 2072.63  178.542072.658   194.7  2075.3   225.3 2076.15
   236.9 2075.68   290.2 2076.17   304.8 2077.67   309.5 2079.21   332.9 2090.93
   341.3 2095.74   360.9 2109.21   365.5 2111.44   384.2 2114.86   388.9 2116.35
   393.5 2118.89   399.3 2123.09   421.5 2134.14   443.3 2142.99     452 2145.89
#Mann= 4 ,-1 , 0
       0      .1       0  116.91      .1       0  149.58    .045       0
  178.54      .1       0
#XS Ineff= 2 , 0
                          201.19         2091.16
Permanent Ineff=
       F       F
Bank Sta=149.58,178.54
XS Rating Curve= 0 ,0
Exp/Cntr=0.3,0.1

Type RM Length L Ch R = 1 ,2198    ,272,271.4,265.8
XS GIS Cut Line= 3
2125991.70571122338180.6907876132126077.12220705338359.857424036
 2126191.7056393338630.690871865
#Sta/Elev= 30
       0 2143.19    12.1  2138.7    23.7 2137.16    37.6 2133.43      63  2122.5
    70.5 2117.83    81.2 2112.85    93.8  2103.2     103 2097.51   127.1 2077.65
   135.7 2073.35   141.9 2072.23  209.38 2071.04     221 2069.93  229.542072.039
   266.1 2072.42   275.9 2073.57   298.6  2079.5   300.8 2080.57   307.9  2087.3
   316.1 2089.06   321.1 2091.39   336.4 2103.75   347.1    2111   372.1 2127.39
   411.2 2150.81   425.5 2157.79   456.3  2170.6   471.8 2176.12   492.6 2182.11
#Mann= 4 ,-1 , 0
       0      .1       0   97.02      .1       0  209.38    .045       0
  229.54      .1       0
Bank Sta=209.38,229.54
XS Rating Curve= 0 ,0
Exp/Cntr=0.3,0.1

Type RM Length L Ch R = 1 ,1926    ,193.9,193.9,193.5
XS GIS Cut Line= 3
2125782.33047378338343.1907906982125887.53892478 338468.19086878
2126050.03892788338665.065803111
#Sta/Elev= 30
       0 2126.07     9.2 2123.52      12 2121.78    23.1 2113.01    34.8 2105.08
    50.6  2091.6    59.2 2082.82    67.4  2072.3    69.7 2070.68      72 2069.57
      86 2070.15  102.842068.675   116.3  2067.5   118.6 2067.65  122.862069.442
     128 2071.58   138.2 2072.54   200.1 2073.02   234.4 2074.54   238.7 2075.13
   251.4 2081.46   258.4  2084.1   282.2 2090.94     294 2092.92     308 2100.14
   330.6 2109.97     345 2116.92   384.2 2134.49   408.9 2144.49   418.7 2147.63
#Mann= 3 ,-1 , 0
       0      .1       0  102.84    .045       0  122.86      .1       0
Bank Sta=102.84,122.86
XS Rating Curve= 0 ,0
Exp/Cntr=0.3,0.1

Type RM Length L Ch R = 1 ,1732    ,306.7,319,318.8
XS GIS Cut Line= 2
2125663.58071131338501.5241354552125922.95552063338796.315868706
#Sta/Elev= 30
       0 2113.97    16.5 2102.13    19.9 2099.32    28.6 2090.06    39.2 2081.24
    41.5 2078.75    46.3 2072.41   51.012068.022    54.8  2067.1    59.2 2066.81
    64.8 2067.41   71.282069.308    78.7 2069.92     102 2069.27   113.6 2070.03
   160.5 2069.79   195.3  2072.5   208.9 2072.88   232.2 2076.04   243.8 2076.62
   254.9 2082.14   269.3 2088.04   284.7 2093.55   289.7 2095.85   306.5  2105.9
   321.4 2113.33   334.4 2121.16   347.6 2127.54   380.9 2140.63   392.7 2144.39
#Mann= 3 ,-1 , 0
       0      .1       0   51.01    .045       0   71.28      .1       0
Bank Sta=51.01,71.28
XS Rating Curve= 0 ,0
Exp/Cntr=0.3,0.1

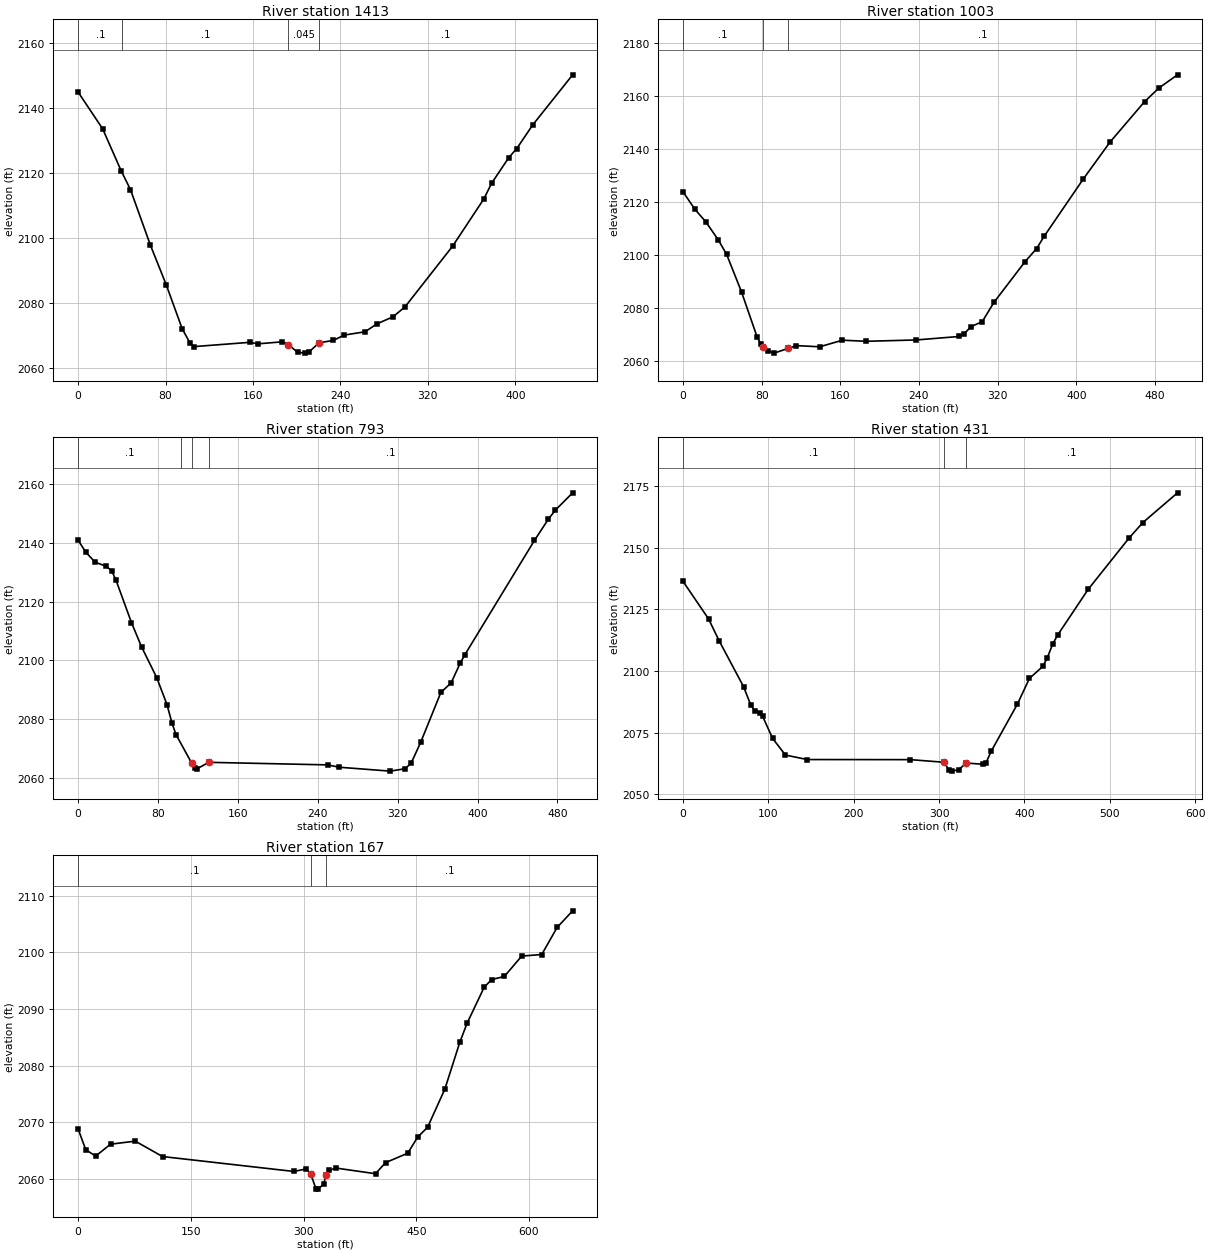
Type RM Length L Ch R = 1 ,1413    ,400.8,409.8,402.6
XS GIS Cut Line= 3
2125478.16375929 338607.773922952125597.95551446338857.774079114
 2125675.0390217339015.065759286
#Sta/Elev= 30
       0 2144.82    22.4 2133.54    39.3 2120.64    47.9 2114.78    66.1 2097.72
    80.6  2085.5    95.2 2071.96   102.4 2067.54   106.1 2066.48     157 2067.79
   164.3 2067.33   186.9 2067.95  192.42 2067.09   200.7 2064.73   207.9 2064.47
   211.6 2064.95  220.482067.648   233.4 2068.38   243.5 2070.03   262.5 2071.04
   273.4 2073.49     288 2075.64     299 2078.69   342.8 2097.49   371.1 2111.91
   378.4 2116.82     394 2124.67   401.3 2127.45   415.9 2134.73   452.4 2150.14
#Mann= 4 ,-1 , 0
       0      .1       0   40.47      .1       0  192.42    .045       0
  220.48      .1       0
Bank Sta=192.42,220.48
XS Rating Curve= 0 ,0
Exp/Cntr=0.3,0.1

Type RM Length L Ch R = 1 ,1003    ,211.4,210.1,208.8
XS GIS Cut Line= 2
2125163.58072704338732.7740010322125443.78882805339150.482483193
#Sta/Elev= 30
       0 2123.78    12.1 2117.18    23.1 2112.51    35.8 2105.69    44.4 2100.15
    59.5 2086.03    75.3  2069.1    79.2 2066.34   81.652065.348    86.7  2063.8
    92.6 2062.94  107.182064.753   115.3 2065.78     139 2065.33   162.2 2067.82
   186.3  2067.4   237.3 2067.91   280.9 2069.22   285.6 2070.07   292.8 2072.89
   304.4 2074.83   316.3  2082.1   347.9 2097.44   359.7 2102.38   367.6 2107.14
   407.1 2128.58   434.5 2142.61   469.5 2157.78   484.2 2162.97     503  2167.9
#Mann= 3 ,-1 , 0
       0      .1       0   81.65    .045       0  107.18      .1       0
Bank Sta=81.65,107.18
XS Rating Curve= 0 ,0
Exp/Cntr=0.3,0.1

Type RM Length L Ch R = 1 ,793     ,345.9,362.8,358.1
XS GIS Cut Line= 2
2124973.99711671 338848.399097862125293.78879997339226.523997784
#Sta/Elev= 30
       0 2140.92     7.8 2136.81      17 2133.45      28 2132.08    33.6  2130.5
    37.9 2127.34    53.4 2112.84    63.5 2104.58    78.8    2094      89 2084.83
      94 2078.54      98 2074.65  113.552065.013   117.2 2063.33   119.5 2063.07
  130.932065.182   249.8 2064.31   261.5 2063.51   312.5 2062.18   327.7 2063.01
   333.7 2065.07     343 2071.99   363.3 2089.06   373.5 2092.26   382.5 2098.94
   387.2 2101.84     457  2140.9     471 2148.18     478 2151.25   495.2 2157.11
#Mann= 4 ,-1 , 0
       0      .1       0   102.8      .1       0  113.55    .045       0
  130.93      .1       0
Bank Sta=113.55,130.93
XS Rating Curve= 0 ,0
Exp/Cntr=0.3,0.1

Type RM Length L Ch R = 1 ,431     ,255.2,263.3,268.5
XS GIS Cut Line= 3
2124839.62238547 338948.399225952124996.91406563339159.857464448
2125177.12236664339419.232273787
#Sta/Elev= 30
       0 2136.35      30 2121.07    42.3 2112.25    70.9 2093.64    79.5 2086.08
    83.9 2083.92    90.5  2082.8    93.3 2081.56     105 2072.63     120 2065.86
   145.5 2064.04   266.5    2064  305.872062.939   311.6 2059.77     315 2059.34
     323 2059.91  331.852062.622   351.7 2062.12     355 2062.71   361.1 2067.41
   391.8 2086.54   405.9 2096.96   421.8 2101.92   426.9 2105.43   433.3 2111.01
   438.9 2114.53   474.8 2133.15   522.7 2153.96   538.7 2160.18   579.4 2172.28
#Mann= 3 ,-1 , 0
       0      .1       0  305.87    .045       0  331.85      .1       0
Bank Sta=305.87,331.85
XS Rating Curve= 0 ,0
Exp/Cntr=0.3,0.1

Type RM Length L Ch R = 1 ,167     ,157.4,167,152.3
XS GIS Cut Line= 2
2124831.51699859339047.7022194932124894.64702201339702.676212485
#Sta/Elev= 30
       0  2068.8    10.1 2065.15    23.3 2064.02    43.1 2066.12      76 2066.66
   112.3 2063.94     287 2061.31   303.5 2061.75   309.7 2060.78   316.6  2058.2
   318.7 2058.19   326.5 2059.01   329.8 2060.65   333.7 2061.49     343 2061.91
   395.7 2060.91     409 2062.86   438.6 2064.53   451.8 2067.37     465 2069.11
     488 2075.86   507.8 2084.09   517.7 2087.52   540.3 2093.82   550.2 2095.18
   567.1 2095.72   590.2 2099.32   616.9  2099.6   637.3 2104.37     658 2107.31
#Mann= 3 , 0 , 0
       0      .1       0   309.7    .045       0   329.8      .1       0
Bank Sta=309.7,329.8
XS Rating Curve= 0 ,0
Exp/Cntr(USF)=0,0
Exp/Cntr=0.3,0.1
LCMann Table=0

Chan Stop Cuts=-1
Use User Specified Reach Order=0
Composite Channel Slope=5